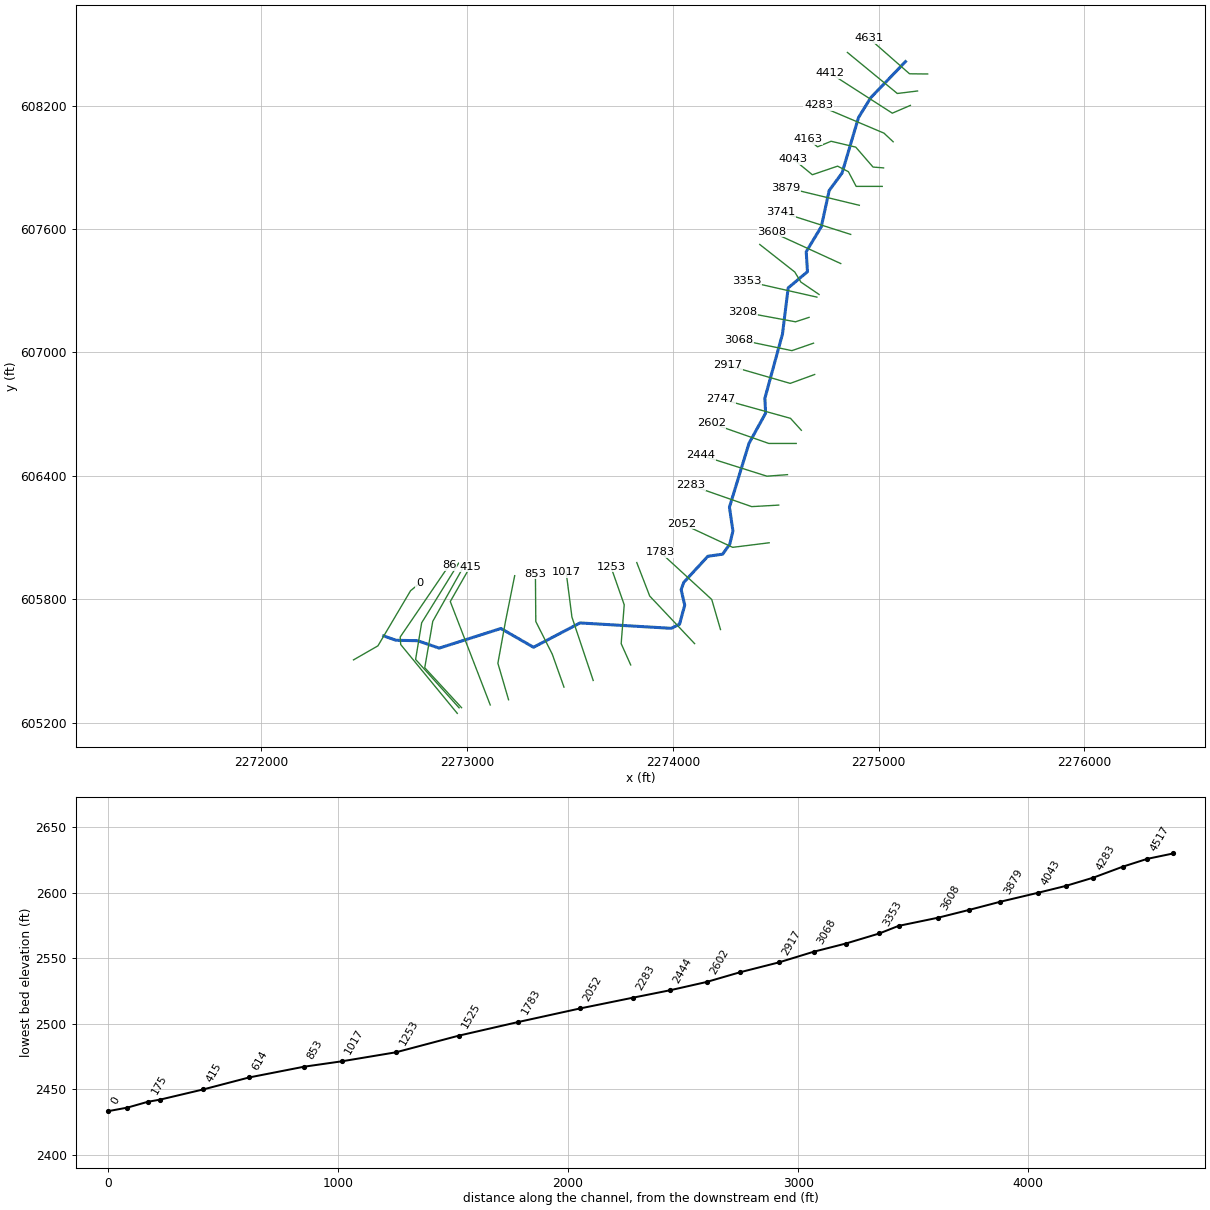
--- BACKFK.prj (project) ---

Proj Title=BACKFK
Current Plan=p01
Default Exp/Contr=0,0
English Units
Geom File=g01
Flow File=f01
Plan File=p01
BEGIN DESCRIPTION:
----------MODEL BY WOOD PLC 2022----------
AFH study
Randolph County, WV
HEC-RAS Version: RAS 6.2
Vertical Datum: NAVD88
Projection: NAD 1983 StatePlane West Virginia S FIPS 4702 (US Feet)
Terrain: 1-meter LIDAR (FEMA Region III 3DEP collected 2016-2018)
Land Use: 2019 NLCD
Hydrologic Method:
WV SIR2010-5033 regression equations
Additional Model Notes:
FACC/dominant flow issue. Will re-evaluate
END DESCRIPTION:
DSS Export Rating Curves= 0
DSS Export Rating Curve Sorted= 0
DSS Export Volume Flow Curves= 0
DXF OffsetX= 0
DXF OffsetY= 0
DXF ScaleX= 0
DXF ScaleY= 0

--- BACKFK.p01 (plan) ---

Plan Title=Floodplain
Program Version=6.20
Short Identifier=Floodplain
Geom File=g01
Flow File=f01
Subcritical Flow
K Sum by GR= 0
Std Step Tol= 0.01
Critical Tol= 0.01
Num of Std Step Trials= 20
Max Error Tol= 0.3
Flow Tol Ratio= 0.001
Split Flow NTrial= 30
Split Flow Tol= 0.02
Split Flow Ratio= 0.02
Log Output Level= 0
Friction Slope Method= 1
Unsteady Friction Slope Method= 2
Unsteady Bridges Friction Slope Method= 1
Parabolic Critical Depth
Global Vel Dist= 0 , 0 , 0
Global Log Level= 0
CheckData=True
Encroach Param=-1 ,0,0, 0
Mapping Interval=1HOUR
Computation Time Step Use Courant=        0
Computation Time Step Use Time Series=    0
Computation Time Step Count To Double=0
Computation Time Step Max Doubling=0
Computation Time Step Max Halving=0
Computation Time Step Residence Courant=0
Run HTab= 0
Run UNet= 0
Run Sediment= 0
Run PostProcess= 0
Run WQNet= 0
Run RASMapper=-1
UNET Theta= 0
UNET Theta Warmup= 0
UNET ZTol= 0
UNET ZSATol= 0
UNET MxIter= 0
UNET Max Iter WO Improvement= 0
UNET MaxInSteps= 0
UNET DtIC= 0
UNET DtMin= 0
UNET MaxCRTS= 0
UNET WFStab= 0
UNET SFStab= 0
UNET WFX= 1
UNET SFX= 1
UNET Gravity=32.174
UNET 1D Methodology=Finite Difference
UNET DSS MLevel= 1
UNET Pardiso=0
UNET DZMax Abort= 0
UNET Use Existing IB Tables= 0
UNET Froude Reduction=False
UNET Froude Limit= 0
UNET Froude Power= 0
UNET D1 Cores= 0
UNET WindReference=Eulerian
UNET WindDragFormulation=Hsu (1988)
UNET D2 Coriolis=0
UNET D2 Cores= 0
UNET D2 Theta= 1
UNET D2 Theta Warmup= 1
UNET D2 Z Tol= 0.01
UNET D2 Volume Tol= 0.01
UNET D2 Max Iterations= 20
UNET D2 Equation= 0
UNET D2 RampUpFraction=0.1
UNET D2 TimeSlices= 1
UNET D2 Turbulence Formulation=Non-Conservative (original)
UNET D2 Eddy Viscosity=0.3
UNET D2 Transverse Eddy Viscosity=0.1
UNET D2 Smagorinsky Mixing=0
UNET D2 BCVolumeCheck=0
UNET D2 Cores=0
UNET D2 SolverType=PARDISO (Direct)
UNET D2 Minimum Iterations= 2147483647
UNET D2 Maximum Iterations= 2147483647
UNET D2 Restart Number= 10
UNET D2 Relaxation Coeff=1.3
UNET D2 SOR Precondition Iterations= 10
UNET D2 ILUT Maximum Fill= 8
UNET D2 ILUT Tolerance=1E-08
UNET D1D2 MaxIter= 0
UNET D1D2 ZTol=0.01
UNET D1D2 QTol=0.1
UNET D1D2 MinQTol=1
Write IC File= 0
Write IC File at Fixed DateTime=0
Write IC File at Sim End=0
Echo Input=False
Echo Parameters=False
Echo Output=False
Write Detailed= 0
HDF Write Warmup=0
HDF Write Time Slices=0
HDF Flush=0
HDF Compression= 1
HDF Chunk Size= 1
HDF Spatial Parts= 1
HDF Use Max Rows=0
HDF Fixed Rows= 1
Calibration Method= 0
Calibration Iterations= 20
Calibration Max Change=0.05
Calibration Tolerance=0.2
Calibration Maximum=1.5
Calibration Minimum=0.5
Calibration Optimization Method= 1
WQ AD Non Conservative
WQ ULTIMATE=-1
WQ Max Comp Step=1HOUR
WQ Output Interval=15MIN
WQ Output Selected Increments= 0
WQ Output face flow=0
WQ Output face velocity=0
WQ Output face area=0
WQ Output face dispersion=0
WQ Output cell volume=0
WQ Output cell surface area=0
WQ Output cell continuity=0
WQ Output cumulative cell continuity=0
WQ Output face conc=0
WQ Output face dconc_dx=0
WQ Output face courant=0
WQ Output face peclet=0
WQ Output face adv mass=0
WQ Output face disp mass=0
WQ Output cell mass=0
WQ Output cell source sink temp=0
WQ Output nsm pathways=0
WQ Output nsm derived pathways=0
WQ Create Restart=0
WQ Fixed Restart=0
WQ System Summary=0
WQ Write To DSS=0
Sorting and Armoring Iterations= 10
XS Update Threshold= 0.02
Bed Roughness Predictor= 0
Hydraulics Update Threshold= 0.02
Energy Slope Method= 1
Volume Change Method= 1
Sediment Retention Method= 0
Sediment TS Multiplier= 1
Warm Up Method= 0
XS Weighting Method= 0
Number of US Weighted Cross Sections= 1
Number of DS Weighted Cross Sections= 1
Upstream XS Weight=0
Main XS Weight=1
Downstream XS Weight=0
Number of DS XS's Weighted with US Boundary= 1
Upstream Boundary Weight= 1
Weight of XSs Associated with US Boundary= 0
Number of US XS's Weighted with DS Boundary= 1
Downstream Boundary Weight= 0.5
Weight of XSs Associated with DS Boundary= 0.5
Percentile Method= 0
Sediment Output Level= 3
Mass or Volume Output= 0
Output Increment Type= 1
Profile and TS Output Increment= 1
Transport Output Increment 1
XS Output Flag= 0
XS Output Increment= 10
Read HDF5 Sediment Hotstart= 0
Sediment Hotstart Type= 0
Write Gradation File= 0
Read Gradation Hotstart= 0
Write HDF5 File= 1
Write Binary Output= 1
Write DSS Sediment File= 0
DSS Sediment Output Type= 1
SV Curve= 0
Specific Gage Flag= 0
Subcell Erosion Methods= 0
Subcell Deposition Methods= 0
Advection Scheme= 1
Matrix Solver= 0
Implicit Weighting Factor= 1
Maximum Outer Loop Convergence Iterations= 5
Convergence Maximum Absolute= 0.001
Convergence RMSE= 0.0001
Grain Fractions Max Abs Error= 0.001
Max Subgrid Regions= 1
Max Subgrid Length Scale= 3.402823E+38
Initial Layer Thickness= 3.402823E+38
Min Layer Thickness= 3.402823E+38
Max Layer Thickness= 3.402823E+38
Number of Layers= 5

--- BACKFK.f01 (steady flow) ---

Flow Title=Flow
Program Version=6.20
Number of Profiles= 1
Profile Names=P100yr
River Rch & RM=BACKFK,Main            ,4631
     425
River Rch & RM=BACKFK,Main            ,1783
     498
River Rch & RM=BACKFK,Main            ,0
    1350
Boundary for River Rch & Prof#=BACKFK,Main            , 1
Up Type= 0
Dn Type= 1
Dn Known WS=2438.3
DSS Import GetInterval= 0
DSS Import GetPeak= 0
DSS Import FillOption= 0

--- BACKFK.g01 (geometry) ---

Geom Title=Geometry
Program Version=6.20

River Reach=BACKFK          ,Main
Reach XY= 30
2275130.96100003608414.121000007      2274961.69608238.339000002
2274902.66200003608142.4190000152274822.36700001607872.019999996
2274759.86700003 607787.385000022274721.67300004607611.603000015
2274648.34900001      607489.7062274654.43600002607392.822999999
     2274560.648607313.8599999992274532.87000002607089.467999995
2274447.36700003 606777.402000012274450.83900003606704.919000015
      2274370.11606558.2179999952274275.05800003606247.887999997
     2274291.985606132.436000019     2274276.794606068.200000003
2274242.07200001606019.589000016     2274170.023606009.173000008
     2274052.836605882.003000006     2274040.249605846.846000016
2274057.60999998605771.759000003     2274032.436605678.878000021
2273992.07199998605658.912000015     2273548.582605685.128000021
2273322.54099998605566.8980000172273163.94700003605658.130999997
2272864.03400002605562.6449999962272758.78200001605598.669000015
     2272653.816      605600.8642272594.20091454605621.997267861

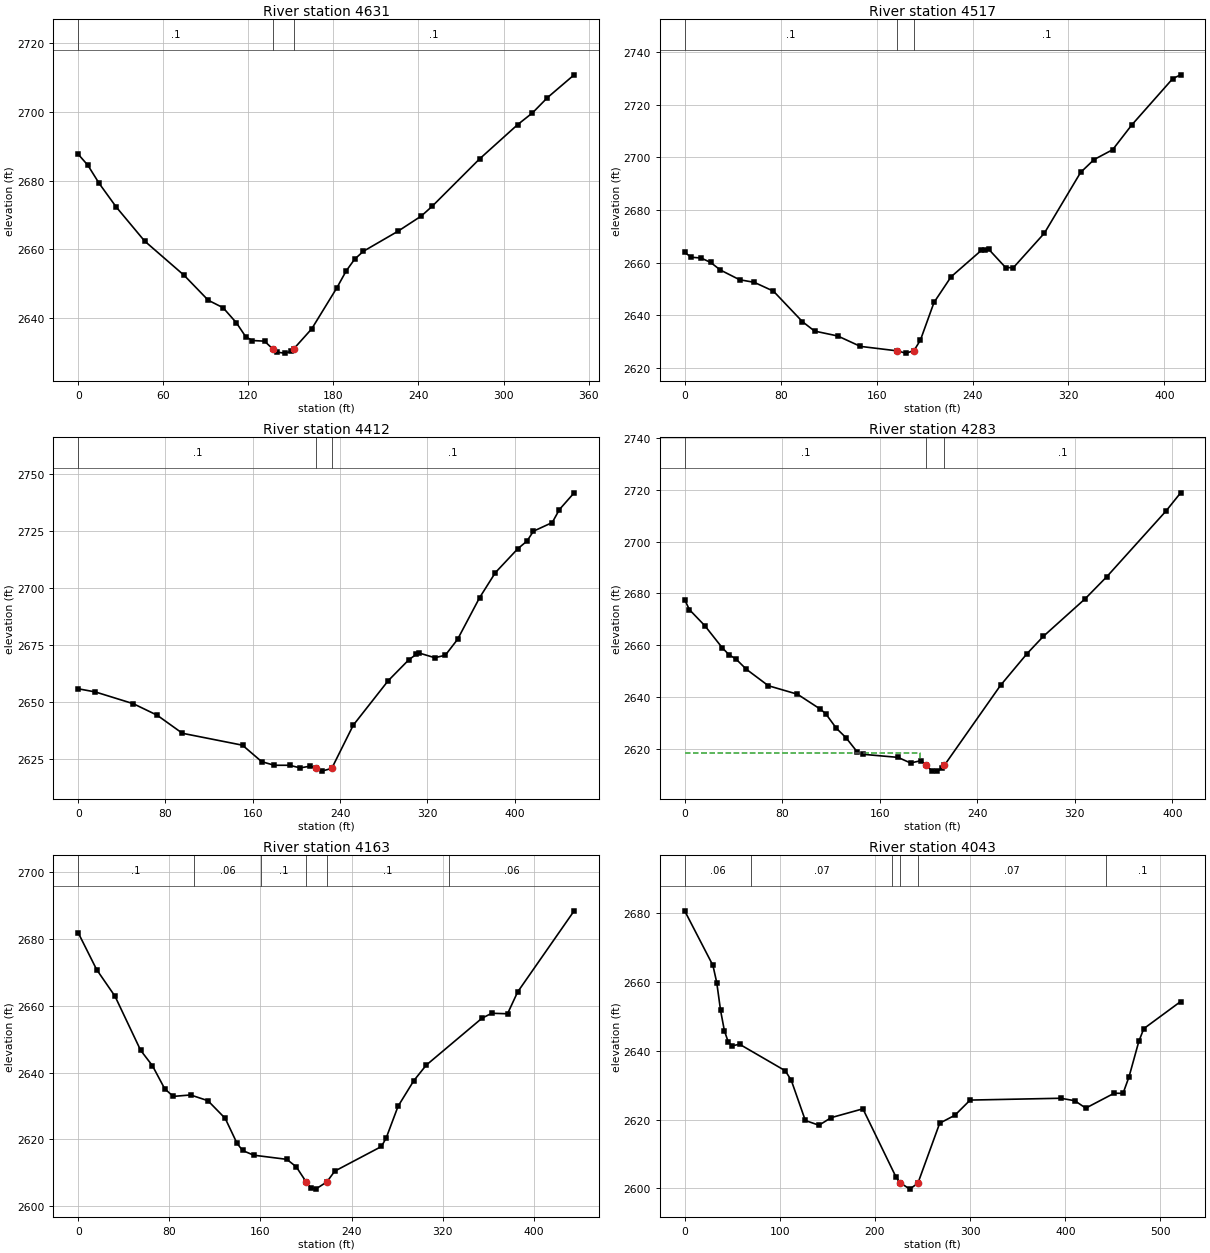
Type RM Length L Ch R = 1 ,4631    ,114.3,114.3,114.6
XS GIS Cut Line= 3
2275238.95091335608353.9048822252275150.51599928608354.868374374
2274954.10301295608527.239627432
#Sta/Elev= 30
       0 2687.64     6.8 2684.45    14.8 2679.16    26.8 2672.32    46.8 2662.44
    74.8 2652.43    91.7 2645.23   102.2 2643.05   111.6 2638.66   118.2 2634.59
   122.9 2633.52   131.4 2633.34   137.1 2631.12   139.9 2630.14   145.6 2629.86
   150.1 2630.34   152.12631.135   164.7 2636.92   182.4 2648.81     189 2653.74
     195 2657.16   201.1 2659.44   225.4 2665.24     242  2669.7   249.6  2672.5
   283.1 2686.29     310 2696.27   320.4 2699.66     331 2704.11   349.8 2710.72
#Mann= 3 ,-1,0
       0      .1       0   137.1    .045       0   152.1      .1       0
Bank Sta=137.1,152.1
XS Rating Curve= 0 ,0
Exp/Cntr(USF)=0,0
Exp/Cntr=0.3,0.1

Type RM Length L Ch R = 1 ,4517    ,103.9,104.8,105.6
XS GIS Cut Line= 3
2275189.62753456608271.2506092942275091.17435955608259.112546622
2274848.41310609608458.716243908
#Sta/Elev= 30
       0  2663.9     5.5 2662.07    13.6 2661.78    21.6 2660.12    29.7 2657.24
    45.8 2653.53    57.9 2652.57      74 2649.21    98.2 2637.61   108.3 2634.05
   127.6 2632.19   146.5 2628.24   177.12626.545   184.3 2625.68   191.1 2626.56
   196.6 2630.68   207.9 2644.94   222.1 2654.64   247.3 2664.67   250.6 2664.97
   253.6 2665.05   267.6 2658.16     274  2658.1   299.9 2671.21   330.1 2694.26
   341.3 2699.14   356.8 2702.88   372.8  2712.3   406.9 2729.85   413.5 2731.31
#Mann= 3 ,-1,0
       0      .1       0   177.1    .045       0   191.1      .1       0
Bank Sta=177.1,191.1
XS Rating Curve= 0 ,0
Exp/Cntr(USF)=0,0
Exp/Cntr=0.3,0.1

Type RM Length L Ch R = 1 ,4412    ,127.1,128.5,129.6
XS GIS Cut Line= 3
2275154.56202017608201.119580518 2275066.8982342608163.356718869
2274764.79534101608357.565721634
#Sta/Elev= 30
       0  2655.9    15.7 2654.52    50.5 2649.36    72.3 2644.33    95.5 2636.39
   150.6 2631.16   168.2 2623.93   179.8 2622.36   193.8 2622.36   203.3 2621.22
   212.8 2621.96   218.3 2620.95   223.2 2619.79   232.42620.981   252.1 2639.93
   284.1 2659.42   303.2 2668.71     310 2671.02   312.7 2671.56   326.9 2669.53
   336.5 2670.62   347.7 2677.56   367.9 2695.85   382.4 2706.86     403 2717.36
   411.3 2720.66   417.3 2725.02   434.5 2728.81   441.1 2734.53   454.6 2741.85
#Mann= 3 ,-1,0
       0      .1       0   218.3    .045       0   232.4      .1       0
Bank Sta=218.3,232.4
XS Rating Curve= 0 ,0
Exp/Cntr(USF)=0,0
Exp/Cntr=0.3,0.1

Type RM Length L Ch R = 1 ,4283    ,119.6,120.4,120.6
BEGIN DESCRIPTION:
Structure XS 4
END DESCRIPTION:
XS GIS Cut Line= 3
2275070.94425509608024.4433349472275026.43802529608066.252217487
2274708.15104854608201.119580518
#Sta/Elev= 30
       0 2677.61     3.8 2673.77    16.6 2667.49    30.8 2659.02    36.4 2656.29
      42 2654.69    50.6 2650.71    68.6 2644.36    92.5 2641.08   111.3  2635.3
   115.7 2633.53   124.3 2627.98   132.2 2624.34   141.7 2618.69   146.1 2617.89
   174.9  2616.7   185.2 2614.54   193.8 2615.42     1982613.624   202.5 2611.58
   206.9 2611.39   211.2 2612.49     2132613.655     259  2644.5   280.7 2656.72
   294.1 2663.41   328.5 2677.97   346.3 2686.52   394.6 2711.74   406.7 2718.83
#Mann= 3 ,-1,0
       0      .1       0     198    .045       0     213      .1       0
#XS Ineff= 2 , 0
          193.04 2618.26
Permanent Ineff=
       F       F
Bank Sta=198,213
XS Rating Curve= 0 ,0
Exp/Cntr(USF)=0,0
Exp/Cntr=0.3,0.1

Type RM Length L Ch R = 1 ,4163    ,121.9,120.4,119
BEGIN DESCRIPTION:
Structure XS 3
END DESCRIPTION:
XS GIS Cut Line= 6
2275024.35703287607897.3823932012274973.10743492607901.428414092
2274889.09518408607998.3781963372274769.45771674608026.855061711
2274703.37270886607999.8815891052274657.51780543608036.295777123
#Sta/Elev= 30
       0  2681.9    16.2 2670.86    32.3 2662.88    54.8 2646.67    65.2 2642.03
      76  2635.1    83.5 2632.84    98.7 2633.27   113.9 2631.55   129.1 2626.24
   139.4 2618.81   144.3 2616.62   154.1 2615.21   183.2 2613.96   191.5 2611.71
   200.1 2607.23   204.3 2605.38   208.5 2605.03   218.32607.181   225.3 2610.43
   266.3 2617.82   270.5 2620.42   280.9  2629.9   294.7 2637.56   305.6 2642.21
   354.5 2656.27   363.1 2657.77     377 2657.62   385.9 2664.17   435.5 2688.49
#Mann= 6 ,-1,0
       0      .1       0  101.41     .06       0  160.75      .1       0
   200.1    .045       0   218.3      .1       0  325.59     .06       0
Bank Sta=200.1,218.3
XS Rating Curve= 0 ,0
Exp/Cntr(USF)=0,0
Exp/Cntr=0.3,0.1

Type RM Length L Ch R = 1 ,4043    ,160.6,163.5,166.1
BEGIN DESCRIPTION:
Structure XS 2
END DESCRIPTION:
XS GIS Cut Line= 6
2275017.91718275607807.422844415 2274891.1418615607807.422844415
2274853.37899985607878.9025468222274800.78072827607905.876019428
2274678.05142791607864.0671368892274586.34162105607939.592860186
#Sta/Elev= 30
       0 2680.65    29.7 2664.78    33.7 2659.81    37.7 2651.75    41.7 2645.86
    45.7  2642.6    49.7 2641.42    57.7 2641.89   105.7 2634.19     112 2631.43
   126.8 2619.74   141.1 2618.36     154 2620.57   187.3 2623.13     222 2603.37
  226.542601.635   236.6  2599.8  245.162601.557     268 2618.95     284 2621.27
     300 2625.67   395.2  2626.2     410 2625.48   421.5 2623.33   451.4 2627.66
   460.7 2627.63     467 2632.45   477.3 2642.74   482.5 2646.42   521.2 2654.29
#Mann= 6 ,-1,0
       0     .06       0      70     .07       0  218.29      .1       0
  226.54    .045       0  245.16     .07       0  442.36      .1       0
Bank Sta=226.54,245.16
XS Rating Curve= 0 ,0
Exp/Cntr(USF)=0,0
Exp/Cntr=0.3,0.1

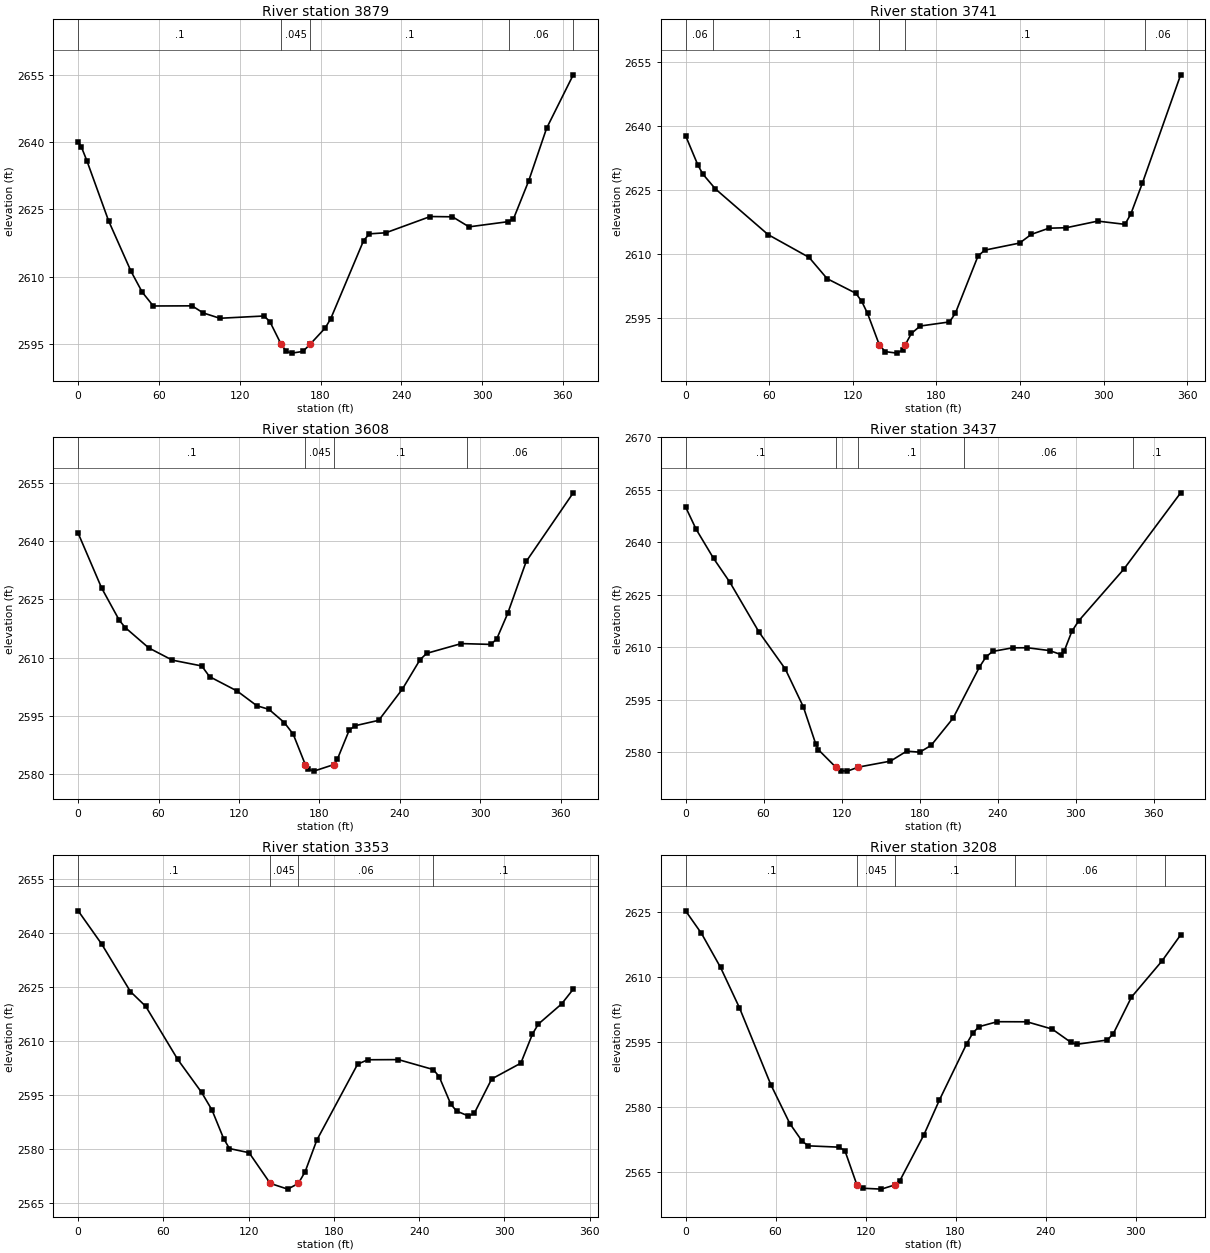
Type RM Length L Ch R = 1 ,3879    ,138.1,137.6,136.9
BEGIN DESCRIPTION:
Structure XS 1
END DESCRIPTION:
XS GIS Cut Line= 2
2274906.40607219607715.5970736052274549.00756016607801.912185945
#Sta/Elev= 30
       0 2640.05     2.3    2639     6.4 2635.92    22.6 2622.47    39.3 2611.19
    47.6 2606.56    55.8 2603.49    84.6 2603.52    92.8 2601.95   105.2 2600.75
   138.1 2601.26   142.4 2599.99  150.812594.921   154.6 2593.36   158.7 2592.98
   166.9 2593.36   172.2 2594.93   183.4 2598.56   187.5  2600.6     212 2618.07
   216.3 2619.57   228.5 2619.81   261.5 2623.43     278 2623.37   290.3 2621.13
   319.2 2622.28   323.3  2622.9   334.6 2631.37   347.9  2643.1   367.7 2655.02
#Mann= 5 ,-1,0
       0      .1       0  150.81    .045       0   172.2      .1       0
     320     .06       0  367.67      .1       0
Bank Sta=150.81,172.2
XS Rating Curve= 0 ,0
Exp/Cntr(USF)=0,0
Exp/Cntr=0.3,0.1

Type RM Length L Ch R = 1 ,3741    ,134,133,132.1
XS GIS Cut Line= 2
2274864.59718965607573.9863424222274526.08010844607681.880232847
#Sta/Elev= 30
       0 2637.73     8.8 2630.86    12.4 2628.71    21.4 2625.23    59.2  2614.5
    88.6 2609.15   101.6 2604.14   122.2 2600.71   126.4 2598.82   130.6 2595.97
     139 2588.62   143.2 2587.01   151.6 2586.65   155.8 2587.37  157.53 2588.55
   162.1  2591.3   168.4 2593.02   189.4 2593.98   193.6 2596.01   209.8 2609.41
   214.6 2610.84   239.7 2612.51   248.1 2614.55   260.7    2616   273.3 2616.12
   295.8 2617.67   315.3 2616.91   319.5 2619.31   327.9 2626.66   355.3 2652.04
#Mann= 5 ,-1,0
       0     .06       0      20      .1       0     139    .045       0
  157.53      .1       0     330     .06       0
Bank Sta=139,157.53
XS Rating Curve= 0 ,0
Exp/Cntr(USF)=0,0
Exp/Cntr=0.3,0.1

Type RM Length L Ch R = 1 ,3608    ,177.4,171.9,167.9
XS GIS Cut Line= 2
2274816.04493896607432.3756112392274480.22520501607586.124405095
#Sta/Elev= 30
       0 2642.03    17.5 2627.93    30.7 2619.61    35.1 2617.75    52.6 2612.52
    70.2 2609.36    92.2 2607.86      98 2605.11   118.6  2601.4   133.3 2597.61
   142.3 2596.69   153.8 2593.27   160.4  2590.3   169.5  2582.4   171.4 2581.27
   175.8 2580.78   190.6 2582.45   193.4 2583.89   202.2 2591.34   206.6 2592.47
   224.2 2593.86   241.9 2601.93     255 2609.46     260 2611.11   285.8 2613.62
   307.8 2613.41   312.2  2614.8   320.4 2621.38   334.2 2634.76   369.3 2652.44
#Mann= 4 ,-1,0
       0      .1       0   169.5    .045       0   190.6      .1       0
     290     .06       0
Bank Sta=169.5,190.6
XS Rating Curve= 0 ,0
Exp/Cntr(USF)=0,0
Exp/Cntr=0.3,0.1

Type RM Length L Ch R = 1 ,3437    ,74.2,83.7,89.5
XS GIS Cut Line= 4
2274710.90097431607281.9833839532274622.51867839607342.184972914
2274592.66314351607391.1959356962274422.50379628607525.077599933
#Sta/Elev= 30
       0 2650.04     8.1 2643.68    21.5 2635.36    34.1  2628.5    56.5 2614.26
    76.7 2603.72    90.6 2592.88   100.1  2582.3   102.1 2580.67  115.48 2575.68
   119.6 2574.64   124.5 2574.53   132.9 2575.68   157.6 2577.39     170 2580.23
   180.2 2579.95   188.9 2581.91   205.7 2589.64     226 2604.26   231.1 2607.21
   236.2 2608.75   251.5 2609.78   262.9  2609.8     280 2608.99   288.6 2607.87
   291.4 2609.01   297.1 2614.48   302.4 2617.51     337 2632.23   380.8 2654.09
#Mann= 5 ,-1,0
       0      .1       0  115.48    .045       0   132.9      .1       0
  214.33     .06       0  344.33      .1       0
Bank Sta=115.48,132.9
XS Rating Curve= 0 ,0
Exp/Cntr(USF)=0,0
Exp/Cntr=0.3,0.1

Type RM Length L Ch R = 1 ,3353    ,143.9,145.1,144.2
XS GIS Cut Line= 2
2274700.05900676607269.1861019712274360.19325192607346.060498899
#Sta/Elev= 30
       0 2646.27    16.6 2636.98    36.8 2623.77    47.6 2619.64    70.1 2604.86
    86.9 2595.68    94.2 2590.78   102.4 2582.82   106.5 2580.04   120.3 2578.89
   135.2 2570.34   147.5 2568.74  154.992570.318   159.8 2573.62     168  2582.4
   196.7 2603.54   203.9 2604.78   225.4 2604.82     250 2602.05   254.1 2600.09
   262.3 2592.41   266.4 2590.48   274.7 2589.12   278.8 2589.83   291.1 2599.43
   311.6 2603.83   319.8 2611.94   323.9 2614.71   340.3 2620.33   348.5 2624.44
#Mann= 4 ,-1,0
       0      .1       0   135.2    .045       0  154.99     .06       0
     250      .1       0
Bank Sta=135.2,154.99
XS Rating Curve= 0 ,0
Exp/Cntr(USF)=0,0
Exp/Cntr=0.3,0.1

Type RM Length L Ch R = 1 ,3208    ,140.2,140.1,139.6
XS GIS Cut Line= 3
2274662.29614511607170.7329269582274596.21113722607149.154148873
2274339.96314746607196.357725934
#Sta/Elev= 30
       0 2625.17    10.6 2619.96    23.3 2612.14    35.9 2602.85    56.8 2585.16
    69.5 2576.17    77.7 2572.11    81.8 2571.04   102.1 2570.74   106.2 2569.96
   114.3 2561.97   118.4 2561.27   130.6 2561.07   139.3 2562.02   142.8 2562.97
   158.9 2573.58   169.2 2581.56   187.5 2594.61   191.6 2597.07   195.6 2598.48
   207.8 2599.63   227.6 2599.61   244.4 2597.94   256.7 2594.93   260.7 2594.42
   281.1 2595.41   285.1 2596.81   297.3  2605.3   317.7 2613.64   330.1 2619.63
#Mann= 5 ,-1,0
       0      .1       0   114.3    .045       0   139.3      .1       0
  219.52     .06       0  319.52      .1       0
Bank Sta=114.3,139.3
XS Rating Curve= 0 ,0
Exp/Cntr(USF)=0,0
Exp/Cntr=0.3,0.1

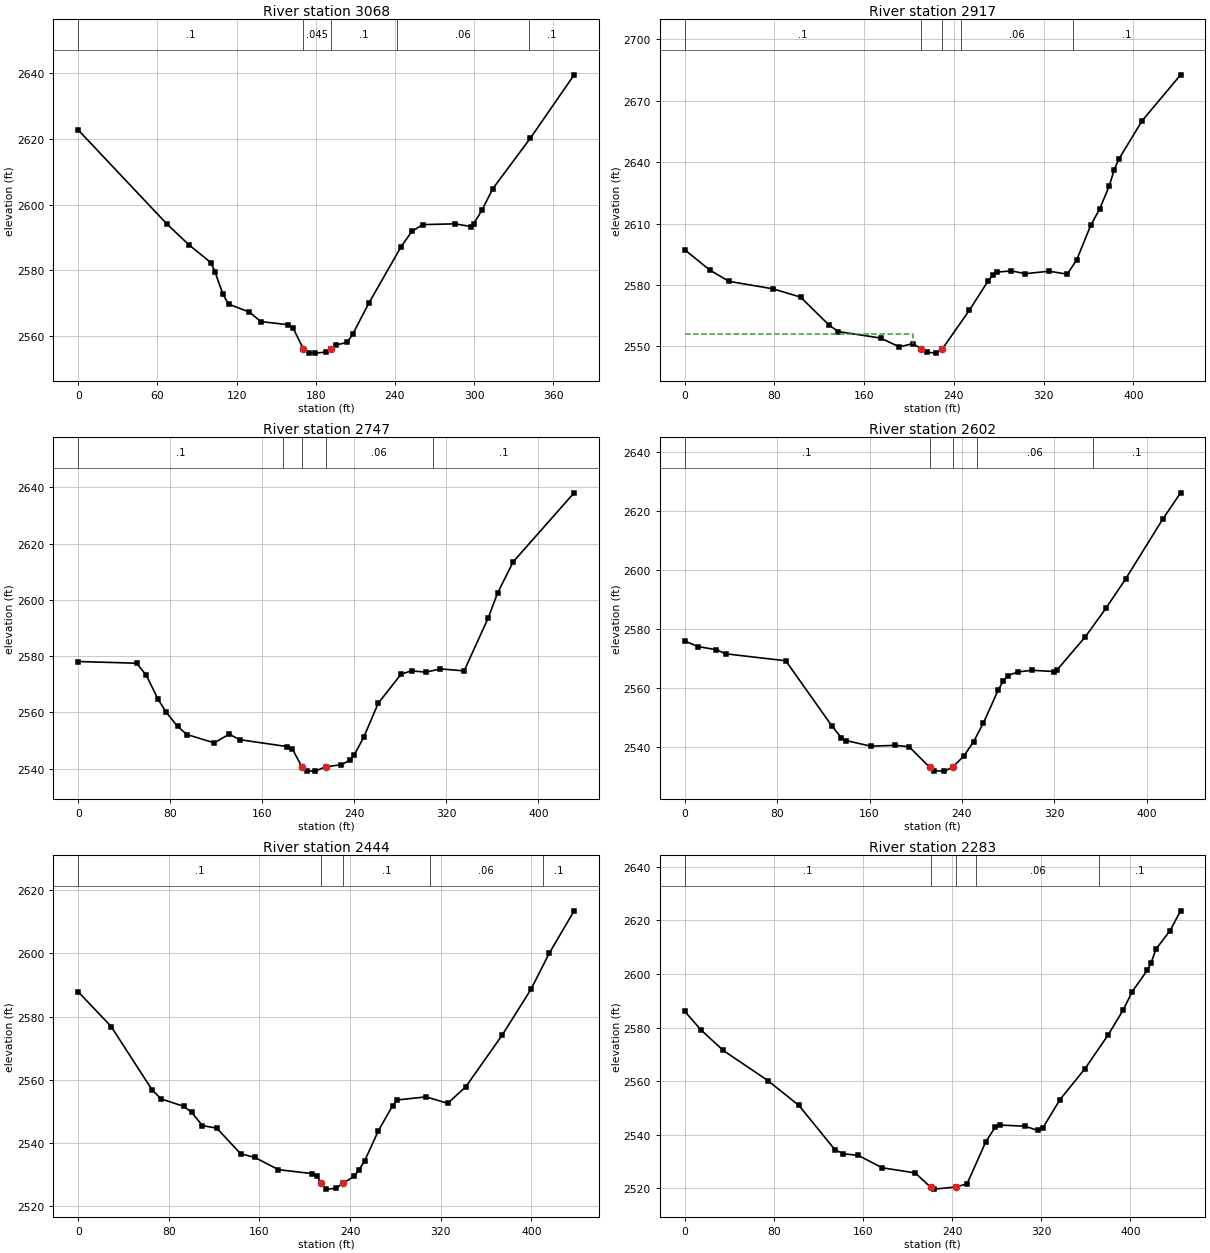
Type RM Length L Ch R = 1 ,3068    ,151.3,150.6,149.9
XS GIS Cut Line= 3
2274683.87492319607045.3062793392274578.67838003607008.892091321
2274319.73304301607062.839036533
#Sta/Elev= 30
       0 2622.69    67.4 2593.99    84.3 2587.61   100.5 2582.35   103.6 2579.55
   109.7 2572.68   113.9 2569.71   129.7 2567.29   138.4 2564.39   158.8 2563.45
   162.9 2562.36   170.62556.064   175.2 2554.86   179.3 2554.79   187.4 2555.08
   191.6 2556.13   195.6 2557.29   203.8 2558.07   207.9 2560.48   220.1  2569.9
   244.6 2587.13   252.8 2591.83     261 2593.89   285.5 2594.13   297.7  2593.3
   299.7  2594.2   305.9 2598.24   314.1  2604.8   342.7 2620.24   375.8 2639.47
#Mann= 5 ,-1,0
       0      .1       0   170.6    .045       0   191.6      .1       0
  241.32     .06       0  341.32      .1       0
Bank Sta=170.6,191.6
XS Rating Curve= 0 ,0
Exp/Cntr(USF)=0,0
Exp/Cntr=0.3,0.1

Type RM Length L Ch R = 1 ,2917    ,169.6,170.4,169.7
XS GIS Cut Line= 3
2274689.26961771606892.9061591142274570.58633824606849.748602944
2274267.13477142606937.412388914
#Sta/Elev= 30
       0 2597.19    22.4 2587.26    39.5 2581.74    78.7 2578.09   103.3 2574.05
   128.8 2560.34   137.1 2557.18   174.6 2554.06   191.3 2549.74   203.7 2551.34
   210.42548.843   216.2 2547.11   224.3 2546.68   229.72548.737   253.8 2567.65
   270.4 2581.86   274.5 2584.76   278.7 2586.27   291.2 2586.84   303.7  2585.5
   324.8 2586.69   341.1 2585.26   349.5 2592.28     362 2609.15   370.1 2617.26
   378.6 2628.57   382.8  2636.1   386.9 2641.35   407.8 2660.21   442.1 2682.64
#Mann= 5 ,-1,0
       0      .1       0   210.4    .045       0   229.7      .1       0
  246.29     .06       0  346.29      .1       0
#XS Ineff= 2 , 0
          203.25 2555.99
Permanent Ineff=
       F       F
Bank Sta=210.4,229.7
XS Rating Curve= 0 ,0
Exp/Cntr(USF)=0,0
Exp/Cntr=0.3,0.1

Type RM Length L Ch R = 1 ,2747    ,144.7,144.6,143.2
XS GIS Cut Line= 3
2274624.53328346606621.8227594212274571.93501188606679.815725524
2274232.06925704606774.222879646
#Sta/Elev= 30
       0 2578.06    50.8 2577.45    59.3 2573.09    69.3 2564.68    76.3 2560.11
    86.3 2554.97    94.6 2552.08   118.2 2549.13   131.2 2552.21   140.3 2550.27
   181.8 2547.79     186 2547.04   194.3 2540.66   198.4 2539.11   205.9 2539.08
     215 2540.61   228.7 2541.36   235.8 2542.87     240 2544.92   248.3 2551.28
   260.7 2563.18   280.6 2573.57   289.8 2574.75   302.2 2574.26   314.7 2575.43
   335.4 2574.73   356.2 2593.45   364.5 2602.45   378.1 2613.55     431 2638.04
#Mann= 5 ,-1,0
       0      .1       0  178.29     .06       0   194.3    .045       0
     215     .06       0  308.29      .1       0
Bank Sta=194.3,215
XS Rating Curve= 0 ,0
Exp/Cntr(USF)=0,0
Exp/Cntr=0.3,0.1

Type RM Length L Ch R = 1 ,2602    ,157.9,158.3,158.5
XS GIS Cut Line= 3
2274599.71509861606557.6784355382274466.51276476606557.678435538
2274187.15787014606655.730153517
#Sta/Elev= 30
       0 2575.82    11.5 2573.94    27.5 2572.85    35.5 2571.47    87.5 2569.11
   127.5 2546.97   135.7 2542.98   139.9 2542.04   161.1 2540.15   182.3 2540.43
   194.3 2539.96     212 2533.02   216.2 2531.81   224.7 2531.69   231.9    2533
   241.7 2536.84   250.1  2541.7   258.6 2548.01   271.3  2559.1   275.8 2562.28
   279.8 2564.08   288.4 2565.34     301 2565.88   319.8 2565.46   322.2 2565.94
   346.9 2577.28   364.6 2586.89   381.6  2596.8   413.9 2617.19   429.3 2626.06
#Mann= 5 ,-1,0
       0      .1       0     212    .045       0   231.9      .1       0
   253.2     .06       0   353.2      .1       0
Bank Sta=212,231.9
XS Rating Curve= 0 ,0
Exp/Cntr(USF)=0,0
Exp/Cntr=0.3,0.1

Type RM Length L Ch R = 1 ,2444    ,160.8,160.4,160.1
XS GIS Cut Line= 3
2274557.16435308606405.9757775332274457.26260268606398.575647875
2274135.35696253606500.327430683
#Sta/Elev= 30
       0 2587.83    29.1 2576.83    65.2 2556.79    73.2 2553.93    93.2 2551.58
   100.2 2549.64   109.7 2545.48   122.3 2544.69   143.3  2536.6   155.9 2535.42
   176.8 2531.54   206.2 2530.31   210.4  2529.7   214.4 2527.29   218.8 2525.39
   227.2 2525.61   233.8 2527.26   243.4 2529.39   248.1 2531.59   252.9 2534.36
   264.9  2543.8   277.5 2551.76   281.7 2553.61   307.1 2554.57   326.2 2552.54
   342.2  2557.8   374.1 2574.02   399.6 2588.56   415.9 2600.06   437.8 2613.44
#Mann= 5 ,-1,0
       0      .1       0   214.4    .045       0   233.8      .1       0
  310.18     .06       0  410.18      .1       0
Bank Sta=214.4,233.8
XS Rating Curve= 0 ,0
Exp/Cntr(USF)=0,0
Exp/Cntr=0.3,0.1

Type RM Length L Ch R = 1 ,2283    ,229.7,231.5,230.2
XS GIS Cut Line= 3
2274514.61360754606257.9731843582274383.26130609606250.573054699
2274087.25611974606354.174869922
#Sta/Elev= 30
       0 2586.07    14.4  2579.2    34.5 2571.49    74.6 2560.25   102.6 2550.93
   134.8 2534.48   142.3 2532.94     156 2532.31   177.2 2527.71   206.9  2525.8
   220.8 2520.48   223.8 2519.75   243.2 2520.53   253.5 2521.73   270.4 2537.49
   278.9 2542.95   283.2 2543.63   305.5 2543.21   317.1 2541.61   321.3 2542.42
   336.9 2553.13   359.4 2564.68   380.1 2577.23   393.7 2586.57   401.8 2593.42
   415.4 2601.43   418.6 2603.91     423 2609.19   435.7 2616.12   445.2 2623.51
#Mann= 5 ,-1,0
       0      .1       0   220.8    .045       0   243.2      .1       0
  261.56     .06       0  371.56      .1       0
Bank Sta=220.8,243.2
XS Rating Curve= 0 ,0
Exp/Cntr(USF)=0,0
Exp/Cntr=0.3,0.1

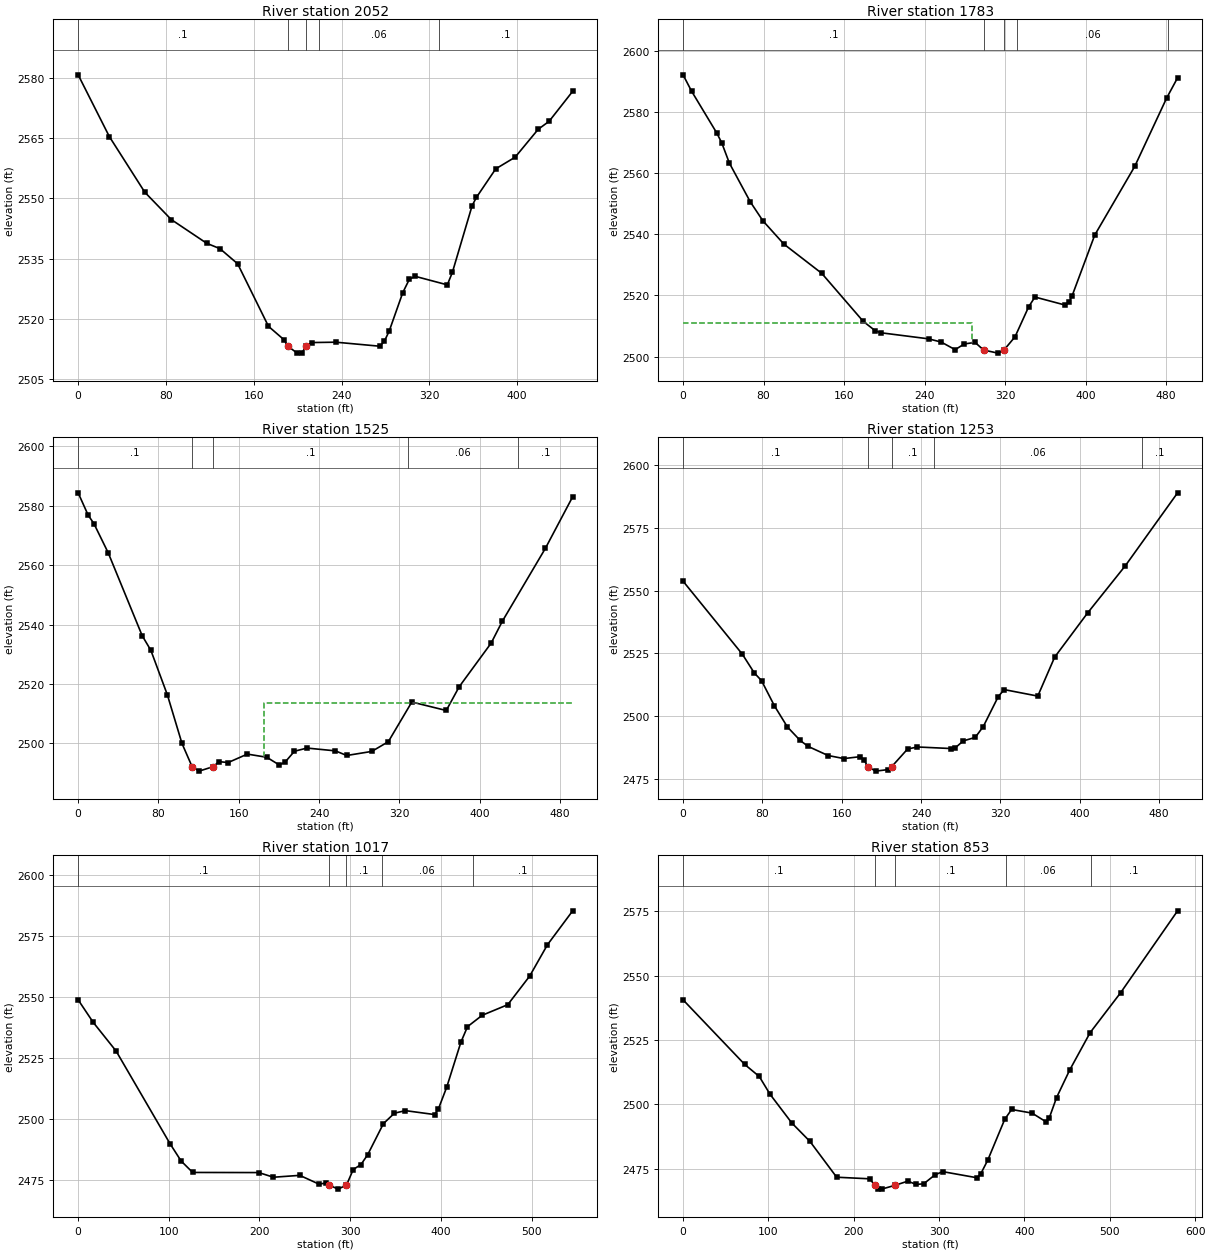
Type RM Length L Ch R = 1 ,2052    ,268.6,268.7,264.7
XS GIS Cut Line= 3
2274468.36279717606074.8199753032274290.75968536606052.619586326
2274044.70537421606167.321596037
#Sta/Elev= 30
       0 2580.69    28.4 2565.34    60.7  2551.5    84.8  2544.7   117.1 2538.79
   129.2 2537.45   145.3 2533.69   173.4 2518.13   187.4 2514.83   191.4 2513.13
   199.5 2511.47   203.9 2511.61   207.82513.158   212.7  2514.1   234.8 2514.19
   274.7 2513.19   278.9 2514.41   283.3 2516.91   295.7  2526.5   301.8 2529.89
   307.2 2530.56   336.3 2528.45   340.9 2531.55   358.9 2548.15   362.8  2550.2
   380.4  2557.3   398.1 2560.21   419.1 2567.15     429 2569.12   450.5 2576.59
#Mann= 5 ,-1,0
       0      .1       0   191.4    .045       0   207.8      .1       0
  218.99     .06       0  328.99      .1       0
Bank Sta=191.4,207.8
XS Rating Curve= 0 ,0
Exp/Cntr(USF)=0,0
Exp/Cntr=0.3,0.1

Type RM Length L Ch R = 1 ,1783    ,253.6,258.1,251.6
XS GIS Cut Line= 3
2274231.55864809605653.0125847522274189.00790255605799.165145513
2273939.25352657606028.569164935
#Sta/Elev= 30
       0 2592.06     8.5 2586.69    33.5 2573.04    38.4 2569.85      46 2563.22
    66.8 2550.54    79.3 2544.36   100.2 2536.73   137.7 2527.21   178.9 2511.52
     191  2508.4   196.6 2507.76   243.9 2505.78   256.5 2504.72   270.3 2502.24
   279.4 2504.11   290.1 2504.61   298.6 2502.12   312.8 2501.11     3192502.198
   329.8 2506.45   343.4 2516.29   349.6 2519.44   379.9 2516.79   383.5 2517.82
   386.4 2519.75     409  2539.7   448.7 2562.12   480.4 2584.46   491.3  2591.1
#Mann= 5 ,-1,0
       0      .1       0   298.6    .045       0     319      .1       0
  332.22     .06       0  482.22      .1       0
#XS Ineff= 2 , 0
          287.36 2510.86
Permanent Ineff=
       F       F
Bank Sta=298.6,319
XS Rating Curve= 0 ,0
Exp/Cntr(USF)=0,0
Exp/Cntr=0.3,0.1

Type RM Length L Ch R = 1 ,1525    ,277.6,272,259.6
XS GIS Cut Line= 3
2274105.75644389605584.5613854082273887.45261896605815.815437245
2273824.55151686605978.618289738
#Sta/Elev= 30
       0 2584.33      10  2576.8    15.7 2573.98    29.9 2564.18    63.8 2536.25
    72.4 2531.35    88.9 2516.32   103.4 2500.02  113.512492.186   120.4  2490.7
   134.5  2492.2   140.2 2493.89   149.4 2493.59   168.5 2496.43   187.9 2495.36
   200.4 2492.75   206.3 2493.81   215.4 2497.39   227.9 2498.46   256.2 2497.52
   267.5 2495.96   292.4 2497.33   308.9  2500.6   332.3 2513.95   366.6  2511.1
   379.5  2519.1   411.3 2533.77   422.4  2541.1   465.3 2565.64   492.5 2583.01
#Mann= 5 ,-1,0
       0      .1       0  113.51    .045       0   134.5      .1       0
  328.02     .06       0  438.02      .1       0
#XS Ineff= 2 , 0
                           185.2         2513.52
Permanent Ineff=
       F       F
Bank Sta=113.51,134.5
XS Rating Curve= 0 ,0
Exp/Cntr(USF)=0,0
Exp/Cntr=0.3,0.1

Type RM Length L Ch R = 1 ,1253    ,231.8,236.5,239.7
XS GIS Cut Line= 4
2273794.95099822605480.9595701852273748.70018785605584.561385408
2273763.50044717605773.2646917072273698.74931266605958.267933177
#Sta/Elev= 30
       0 2553.77    59.8 2524.65    71.9 2517.15    79.1 2514.13    92.2 2504.02
   105.2 2495.66   118.1 2490.27   126.1  2487.9   146.2 2484.27   162.2 2483.04
   178.3 2483.79   182.3 2482.67   186.3 2479.79   194.3 2478.04   206.4 2478.63
   210.4 2479.82   226.4 2486.85   236.3 2487.67   270.6 2487.04   274.6 2487.37
   282.6  2490.1   294.6 2491.48   302.7 2495.78   317.8 2507.72   323.8 2510.55
   357.7 2507.96   374.7 2523.47     408 2541.13     446 2559.93   498.7    2589
#Mann= 5 ,-1,0
       0      .1       0   186.3    .045       0   210.4      .1       0
  253.46     .06       0  462.74      .1       0
Bank Sta=186.3,210.4
XS Rating Curve= 0 ,0
Exp/Cntr(USF)=0,0
Exp/Cntr=0.3,0.1

Type RM Length L Ch R = 1 ,1017    ,161.3,163.1,163.6
XS GIS Cut Line= 3
2273612.64129583 605405.456977682273509.34844712605713.522696629
 2273481.1820695605932.171711111
#Sta/Elev= 30
       0 2548.77    16.6 2539.54    41.9 2527.74   101.3 2489.77   113.6 2482.65
   126.3 2477.96   199.2 2477.91   215.4    2476   244.4 2476.77   265.5 2473.19
   273.9 2473.63  276.682472.819   286.6 2471.12  295.912472.762   303.4 2479.17
   311.9  2481.2   319.3 2485.22   336.7    2498   348.8 2502.27   360.9 2503.32
   393.1 2501.71   397.2 2503.91   406.5 2512.96   422.1 2531.38   429.4 2537.76
   445.6 2542.43   473.8 2546.78     498 2558.52   517.6 2571.38   545.4 2585.28
#Mann= 5 ,-1,0
       0      .1       0  276.68    .045       0  295.91      .1       0
  334.92     .06       0  434.92      .1       0
Bank Sta=276.68,295.91
XS Rating Curve= 0 ,0
Exp/Cntr(USF)=0,0
Exp/Cntr=0.3,0.1

Type RM Length L Ch R = 1 ,853     ,246.5,239.4,231.6
XS GIS Cut Line= 4
2273470.68320146605373.0739801842273413.62717209605533.509552536
2273333.62133027605692.0925604282273331.78338723605923.635744342
#Sta/Elev= 30
       0 2540.64    72.3  2515.5    89.3 2510.83     102 2503.88   127.5 2492.73
   148.7 2485.58     180 2471.66   218.8 2471.04   224.7 2468.52   228.2 2467.18
   232.6 2467.03   248.5 2468.52   263.4 2470.14     273 2468.86   281.9 2469.09
   295.4 2472.63   304.3 2473.83   344.6 2471.44     349  2473.1     357 2478.27
     377 2494.22     385    2498     409 2496.59     425 2493.27     429 2494.61
   437.7 2502.65     453 2513.31     477 2527.88   512.9 2543.48   579.5 2575.25
#Mann= 5 ,-1,0
       0      .1       0   224.7    .045       0   248.5      .1       0
   377.9     .06       0   477.9      .1       0
Bank Sta=224.7,248.5
XS Rating Curve= 0 ,0
Exp/Cntr(USF)=0,0
Exp/Cntr=0.3,0.1

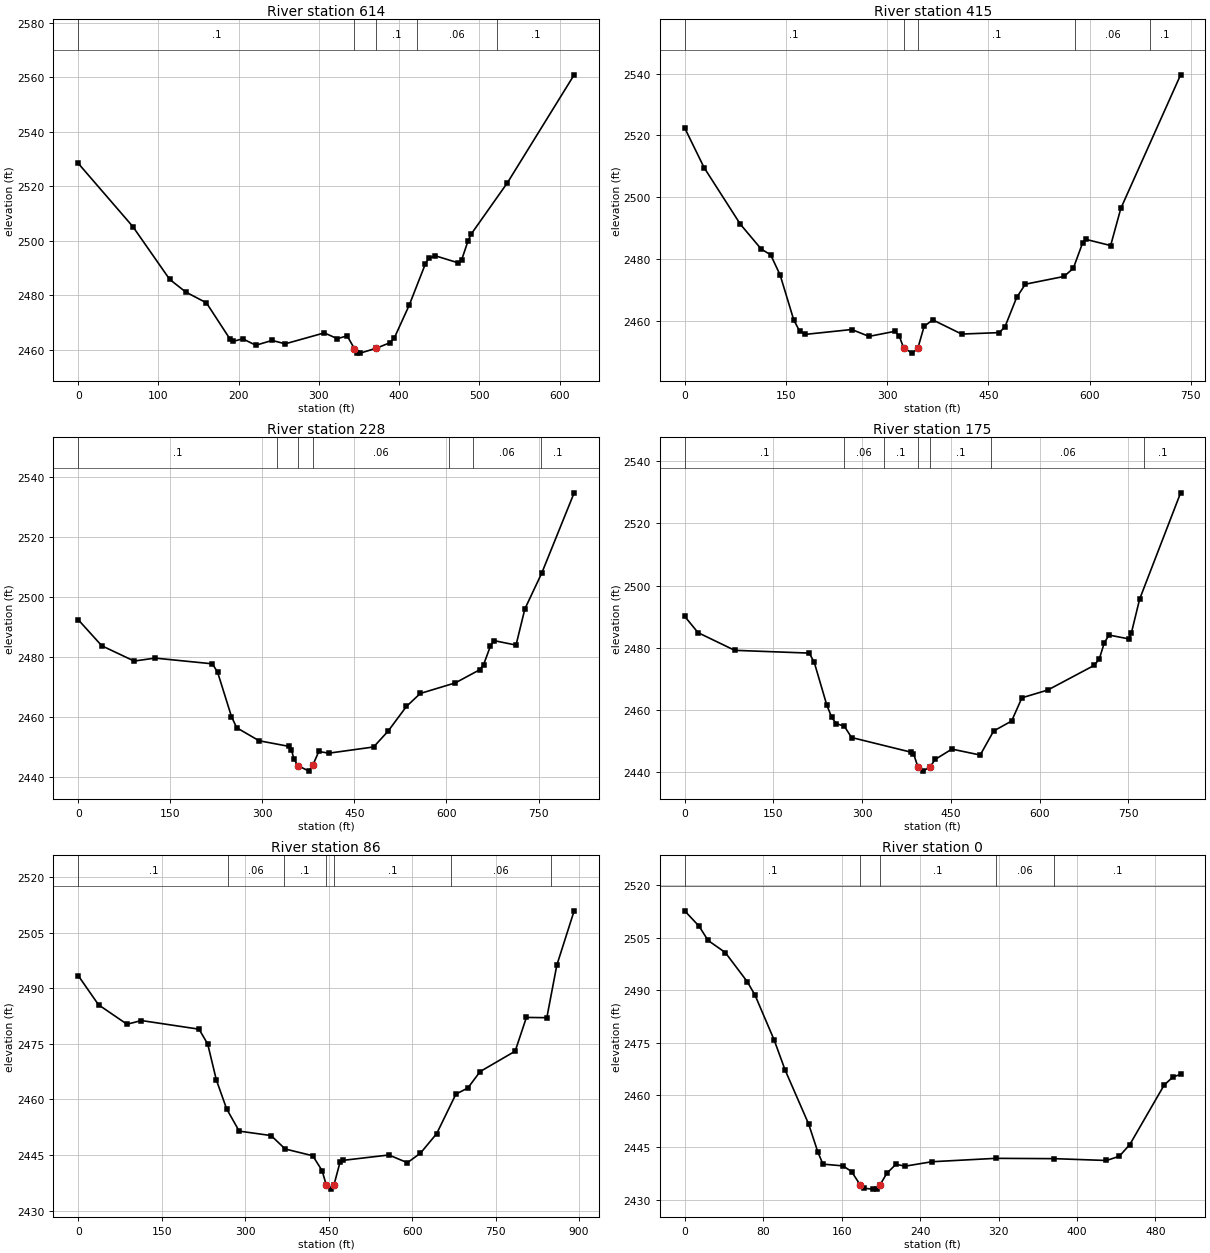
Type RM Length L Ch R = 1 ,614     ,193.8,199.3,208.7
XS GIS Cut Line= 4
2273201.17173235605311.7939874162273149.32215893605489.220604386
2273186.46772835605693.5212361752273230.99483898605914.834868807
#Sta/Elev= 30
       0 2528.45    68.1 2505.23     114 2485.86   134.1 2481.21   159.8 2477.25
   188.9 2464.09   192.9 2463.09   205.1 2464.04   221.4 2461.68   241.7 2463.46
     258  2462.2   306.8 2466.22     323 2464.09   335.2 2465.13   344.3 2460.45
   347.4 2458.93   351.5 2458.79   371.8 2460.61   388.1 2462.55   393.7 2464.16
   412.5 2476.32   432.9 2491.65     437  2493.6   445.2 2494.51   473.8 2491.91
   477.8 2492.86     486 2500.06   490.1 2502.58     535 2521.31   618.2 2560.93
#Mann= 5 ,-1,0
       0      .1       0   344.3    .045       0   371.8      .1       0
   422.5     .06       0   522.5      .1       0
Bank Sta=344.3,371.8
XS Rating Curve= 0 ,0
Exp/Cntr(USF)=0,0
Exp/Cntr=0.3,0.1

Type RM Length L Ch R = 1 ,415     ,194.8,187,183.2
BEGIN DESCRIPTION:
Structure XS 4
END DESCRIPTION:
XS GIS Cut Line= 3
2273112.17658952605286.3486483442272917.87668796605789.242511208
2273015.02663874605959.254925074
#Sta/Elev= 30
       0 2522.45    28.8  2509.6    82.6 2491.28   113.5 2483.27   127.4 2481.43
   141.4 2474.92   161.7 2460.33   170.3 2456.78   178.8 2455.71   247.5 2457.28
   273.2 2455.06   311.5  2456.7   317.7 2455.29   324.6 2451.27   337.5 2449.65
   345.5 2451.24   354.8 2458.28   367.5 2460.41   410.4 2455.81   466.2 2456.28
   474.7  2458.2   491.9 2467.63   504.8 2471.93   562.1 2474.43   575.9 2477.07
   589.7  2485.3   594.3 2486.43   631.2 2484.42   646.3 2496.43   734.9  2539.6
#Mann= 5 ,-1,0
       0      .1       0   324.6    .045       0   345.5      .1       0
  579.12     .06       0  689.12      .1       0
Bank Sta=324.6,345.5
XS Rating Curve= 0 ,0
Exp/Cntr(USF)=0,0
Exp/Cntr=0.3,0.1

Type RM Length L Ch R = 1 ,228     ,53.9,53,53.2
BEGIN DESCRIPTION:
Structure XS 3
END DESCRIPTION:
XS GIS Cut Line= 4
2272972.85010964605272.9667642212272793.74712249605467.327741127
2272832.78572232605693.059131902 2272987.1901932605967.151469371
#Sta/Elev= 30
       0 2492.41    38.4 2483.71    91.2 2478.61   125.2  2479.6   218.6 2477.69
   227.1 2474.89   249.7 2460.08   258.2 2456.37   294.6 2452.03   343.3 2450.15
   347.4 2449.01   351.4 2445.93   357.82443.741   375.8 2441.89     3822443.813
     392 2448.44   408.3 2447.88   481.3 2449.95   504.8 2455.21   534.8 2463.48
   557.3  2467.8   614.4 2471.33   654.2 2475.72   660.4 2477.37   671.4 2483.52
   677.2 2485.44   713.3 2483.94   727.7 2496.01   755.2 2507.96     808 2534.74
#Mann= 7 ,-1,0
       0      .1       0   324.3     .06       0   357.8    .045       0
     382     .06       0  603.38      .1       0  643.38     .06       0
  753.38      .1       0
Bank Sta=357.8,382
XS Rating Curve= 0 ,0
Exp/Cntr(USF)=0,0
Exp/Cntr=0.3,0.1

Type RM Length L Ch R = 1 ,175     ,86.5,89,90.6
BEGIN DESCRIPTION:
Structure XS 2
END DESCRIPTION:
XS GIS Cut Line= 4
 2272960.7466724605272.4050269882272749.27293245605507.719021467
2272778.83059161605685.9153368962272958.74333265605976.060277704
#Sta/Elev= 30
       0 2490.08    22.6 2484.82    84.6 2479.13   210.6 2478.24   219.1 2475.23
   240.2 2461.54   248.4 2457.63   255.9 2455.58     270 2454.68   282.1 2451.07
   382.8 2446.34   386.8 2445.87  394.26 2441.67     403 2440.25   415.12441.666
   423.3    2444   451.7 2447.34   499.6 2445.43   522.3 2453.16   552.7 2456.38
   570.1 2463.85   613.8 2466.35   692.1 2474.27   700.8  2476.3   709.5  2481.6
   717.4 2484.05   750.3 2482.83     755 2484.59   769.1 2495.61   838.4 2529.83
#Mann= 7 ,-1,0
       0      .1       0     270     .06       0  336.38      .1       0
  394.26    .045       0   415.1      .1       0  517.01     .06       0
  777.01      .1       0
Bank Sta=394.26,415.1
XS Rating Curve= 0 ,0
Exp/Cntr(USF)=0,0
Exp/Cntr=0.3,0.1

Type RM Length L Ch R = 1 ,86      ,91.2,85.3,81.1
BEGIN DESCRIPTION:
Structure XS 1
END DESCRIPTION:
XS GIS Cut Line= 4
 2272951.8662343 605245.438201112272676.91967054605579.878266135
2272674.38363998 605616.740226042272911.85241133605964.742736794
#Sta/Elev= 30
       0 2493.41    36.5 2485.53    87.7 2480.28   113.6 2481.28   217.1 2478.95
   232.7 2474.94   248.2 2465.27   266.7 2457.45   289.3 2451.45   346.6 2450.25
   371.9 2446.63   421.5  2444.8   438.3 2440.77  445.88 2436.82   454.3  2435.8
   459.4 2436.83   470.4 2443.03   475.3 2443.55   558.2 2445.01   591.5 2442.93
     615  2445.5   644.2 2450.78   678.7 2461.43   700.2 2463.08   722.2 2467.51
   785.2 2473.02   805.4 2482.12   842.1 2482.05   860.1 2496.24   891.2 2510.88
#Mann= 7 ,-1,0
       0      .1       0     270     .06       0     370      .1       0
  445.88    .045       0   459.4      .1       0   669.9     .06       0
   849.9      .1       0
Bank Sta=445.88,459.4
XS Rating Curve= 0 ,0
Exp/Cntr(USF)=0,0
Exp/Cntr=0.3,0.1

Type RM Length L Ch R = 1 ,0       ,277.1,268.7,261.7
XS GIS Cut Line= 4
2272447.36157977605505.4408138432272566.10683257605573.701557968
2272724.79005475605841.7233902632272769.09176399605878.046252423
#Sta/Elev= 30
       0 2512.72    14.8 2508.28    23.8 2504.25    41.4 2500.78    63.7 2492.47
    71.7  2488.6    91.2 2475.76   102.4 2467.14   126.4 2451.67   135.9 2443.56
     141 2440.19   161.5 2439.68   170.2 2438.05   178.7 2434.35   182.8 2433.26
   192.1 2433.03   196.5 2433.19  199.43 2434.35   206.1 2437.56   215.4 2440.14
   224.7  2439.6     252 2440.87  316.972441.845  376.972441.756   430.1 2441.23
   443.2 2442.44   453.9  2445.8     489 2462.87   498.1 2465.19   505.7 2465.86
#Mann= 5 ,-1,0
       0      .1       0   178.7    .045       0  199.43      .1       0
  316.97     .06       0  376.97      .1       0
Bank Sta=178.7,199.43
XS Rating Curve= 0 ,0
Exp/Cntr=0.3,0.1
LCMann Table=0

Chan Stop Cuts=-1
Use User Specified Reach Order=0
Composite Channel Slope=5